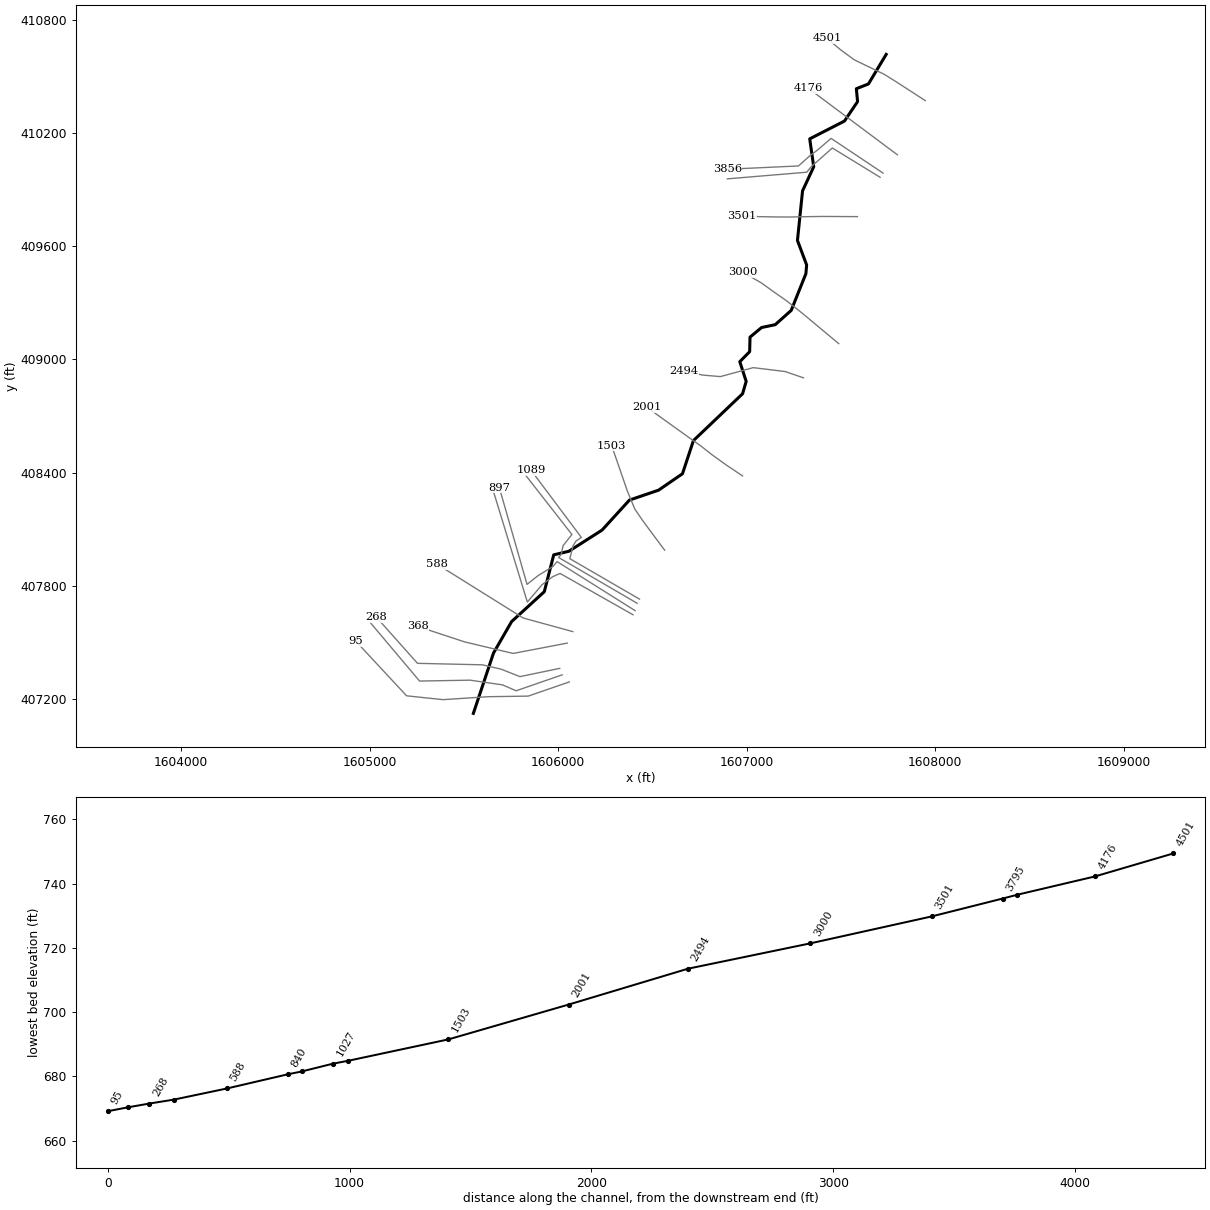
--- DEURRSRN.prj (project) ---

Proj Title=DEURRSRN
Current Plan=p01
Default Exp/Contr=0,0
English Units
Geom File=g01
Flow File=f01
Plan File=p01
BEGIN DESCRIPTION:
---------- MODELED AS PART OF WVEMD CTP PROGRAM, 2023----------
Stream Name: Deurrs Run
Flood Zone:  AFH
Wetzel County, WV
HEC-RAS Version: RAS 6.3
Vertical Datum: NAVD88
Projection: NAD 1983 StatePlane West Virginia S FIPS 4702 (US Feet)
Terrain: 1-meter West Virginia FEMA R3 South Central (collected 2018-2020)
Land Use: 2019 NLCD
Hydrologic Method:
WV SIR2010-5033 regression equations
Additional Model Notes:
Leveraged XS
END DESCRIPTION:
DSS Export Rating Curves= 0
DSS Export Rating Curve Sorted= 0
DSS Export Volume Flow Curves= 0
DXF OffsetX= 0
DXF OffsetY= 0
DXF ScaleX= 0
DXF ScaleY= 0

--- DEURRSRN.p01 (plan) ---

Plan Title=Floodplain
Program Version=6.30
Geom File=g01
Flow File=f01
Subcritical Flow
K Sum by GR= 0
Std Step Tol= 0.01
Critical Tol= 0.01
Num of Std Step Trials= 20
Max Error Tol= 0.3
Flow Tol Ratio= 0.001
Split Flow NTrial= 30
Split Flow Tol= 0.02
Split Flow Ratio= 0.02
Log Output Level= 0
Friction Slope Method= 1
Unsteady Friction Slope Method= 2
Unsteady Bridges Friction Slope Method= 1
Parabolic Critical Depth
Global Vel Dist= 0 , 0 , 0
Global Log Level= 0
CheckData=True
Encroach Param=-1 ,0,0, 0
Mapping Interval=1HOUR
Computation Time Step Use Courant=        0
Computation Time Step Use Time Series=    0
Computation Time Step Count To Double=0
Computation Time Step Max Doubling=0
Computation Time Step Max Halving=0
Computation Time Step Residence Courant=0
Run HTab= 0
Run UNet= 0
Run Sediment= 0
Run PostProcess= 0
Run WQNet= 0
Run RASMapper= 0
UNET Theta= 0
UNET Theta Warmup= 0
UNET ZTol= 0
UNET ZSATol= 0
UNET MxIter= 0
UNET Max Iter WO Improvement= 0
UNET MaxInSteps= 0
UNET DtIC= 0
UNET DtMin= 0
UNET MaxCRTS= 0
UNET WFStab= 0
UNET SFStab= 0
UNET WFX= 1
UNET SFX= 1
UNET Gravity=32.17405
UNET 1D Methodology=Finite Difference
UNET DSS MLevel= 1
UNET Pardiso=0
UNET DZMax Abort= 0
UNET Use Existing IB Tables= 0
UNET Froude Reduction=False
UNET Froude Limit= 0
UNET Froude Power= 0
UNET D1 Cores= 0
UNET WindReference=Eulerian
UNET WindDragFormulation=Hsu (1988)
UNET D2 Coriolis=0
UNET D2 Cores= 0
UNET D2 Theta= 1
UNET D2 Theta Warmup= 1
UNET D2 Z Tol= 0.01
UNET D2 Volume Tol= 0.01
UNET D2 Max Iterations= 20
UNET D2 Equation= 0
UNET D2 RampUpFraction=0.1
UNET D2 TimeSlices= 1
UNET D2 Turbulence Formulation=Non-Conservative (original)
UNET D2 Eddy Viscosity=0.3
UNET D2 Transverse Eddy Viscosity=0.1
UNET D2 Smagorinsky Mixing=0
UNET D2 BCVolumeCheck=0
UNET D2 Cores=0
UNET D2 SolverType=PARDISO (Direct)
UNET D2 Minimum Iterations= 3
UNET D2 Maximum Iterations= 30
UNET D2 Restart Number= 10
UNET D2 Relaxation Coeff=1.3
UNET D2 SOR Precondition Iterations= 10
UNET D2 ILUT Maximum Fill= 8
UNET D2 ILUT Tolerance=1E-08
UNET D2 Convergence Tolerance=0.00001
UNET D1D2 MaxIter= 0
UNET D1D2 ZTol=0.01
UNET D1D2 QTol=0.1
UNET D1D2 MinQTol=1
Write IC File= 0
Write IC File at Fixed DateTime=0
Write IC File at Sim End=0
Echo Input=False
Echo Parameters=False
Echo Output=False
Write Detailed= 0
HDF Write Warmup=0
HDF Write Time Slices=0
HDF Flush=0
HDF Compression= 1
HDF Chunk Size= 1
HDF Spatial Parts= 1
HDF Use Max Rows=0
HDF Fixed Rows= 1
Calibration Method= 0
Calibration Iterations= 20
Calibration Max Change=0.05
Calibration Tolerance=0.2
Calibration Maximum=1.5
Calibration Minimum=0.5
Calibration Optimization Method= 1
WQ AD Non Conservative
WQ ULTIMATE=-1
WQ Max Comp Step=1HOUR
WQ Output Interval=15MIN
WQ Output Selected Increments= 0
WQ Output face flow=0
WQ Output face velocity=0
WQ Output face area=0
WQ Output face dispersion=0
WQ Output cell volume=0
WQ Output cell surface area=0
WQ Output cell continuity=0
WQ Output cumulative cell continuity=0
WQ Output face conc=0
WQ Output face dconc_dx=0
WQ Output face courant=0
WQ Output face peclet=0
WQ Output face adv mass=0
WQ Output face disp mass=0
WQ Output cell mass=0
WQ Output cell source sink temp=0
WQ Output nsm pathways=0
WQ Output nsm derived pathways=0
WQ Create Restart=0
WQ Fixed Restart=0
WQ System Summary=0
WQ Write To DSS=0
Sorting and Armoring Iterations= 10
XS Update Threshold= 0.02
Bed Roughness Predictor= 0
Hydraulics Update Threshold= 0.02
Energy Slope Method= 1
Volume Change Method= 1
Sediment Retention Method= 0
Sediment TS Multiplier= 1
Warm Up Method= 0
XS Weighting Method= 0
Number of US Weighted Cross Sections= 1
Number of DS Weighted Cross Sections= 1
Upstream XS Weight=0
Main XS Weight=1
Downstream XS Weight=0
Number of DS XS's Weighted with US Boundary= 1
Upstream Boundary Weight= 1
Weight of XSs Associated with US Boundary= 0
Number of US XS's Weighted with DS Boundary= 1
Downstream Boundary Weight= 0.5
Weight of XSs Associated with DS Boundary= 0.5
Percentile Method= 0
Sediment Output Level= 3
Mass or Volume Output= 0
Output Increment Type= 1
Profile and TS Output Increment= 1
Transport Output Increment 1
XS Output Flag= 0
XS Output Increment= 10
Read HDF5 Sediment Hotstart= 0
Sediment Hotstart Type= 0
Write Gradation File= 0
Read Gradation Hotstart= 0
Write HDF5 File= 1
Write Binary Output= 1
Write DSS Sediment File= 0
DSS Sediment Output Type= 1
SV Curve= 0
Specific Gage Flag= 0
Subcell Erosion Methods= 0
Subcell Deposition Methods= 0
Advection Scheme= 1
Matrix Solver= 0
Implicit Weighting Factor= 1
Maximum Outer Loop Convergence Iterations= 5
Convergence Maximum Absolute= 0.001
Convergence RMSE= 0.0001
Grain Fractions Max Abs Error= 0.001
Max Subgrid Regions= 1
Max Subgrid Length Scale= 3.402823E+38
Initial Layer Thickness= 3.402823E+38
Min Layer Thickness= 3.402823E+38
Max Layer Thickness= 3.402823E+38
Number of Layers= 5

--- DEURRSRN.f01 (steady flow) ---

Flow Title=Flow
Program Version=4.00
Number of Profiles=1
Profile Names=F01pct
River Rch & RM=DEURRSRN,Main,4501
     656
River Rch & RM=DEURRSRN,Main,2001
     737
Boundary for River Rch & Prof#=DEURRSRN,Main      ,1
Up Type=0
Dn Type=3
Dn Slope=0.018441

--- DEURRSRN.g01 (geometry) ---

Geom Title=Geometry
Program Version=6.31

River Reach=DEURRSRN        ,Main
Reach XY= 30
1607739.48306443 410618.36720939     1607645.312      410461.497
     1607581.167      410436.228     1607587.776      410367.806
     1607518.188      410264.785     1607333.916      410170.317
     1607355.112      410022.185     1607295.896      409894.547
     1607268.776       409631.56     1607317.542      409501.435
     1607313.561      409455.157     1607235.685      409260.343
     1607151.091      409184.706      1607078.44      409169.529
     1607017.234      409118.524     1607015.244      409041.394
     1606962.994      408988.399     1606996.832        408883.9
     1606977.674      408818.216     1606716.926      408569.659
     1606658.954      408394.003     1606531.815      408306.672
     1606377.555408254.221378075     1606232.253      408094.939
     1606056.348      407982.728     1605975.984      407963.818
     1605925.974      407768.257     1605752.556      407609.768
     1605656.518       407442.82      1605549.69      407122.836

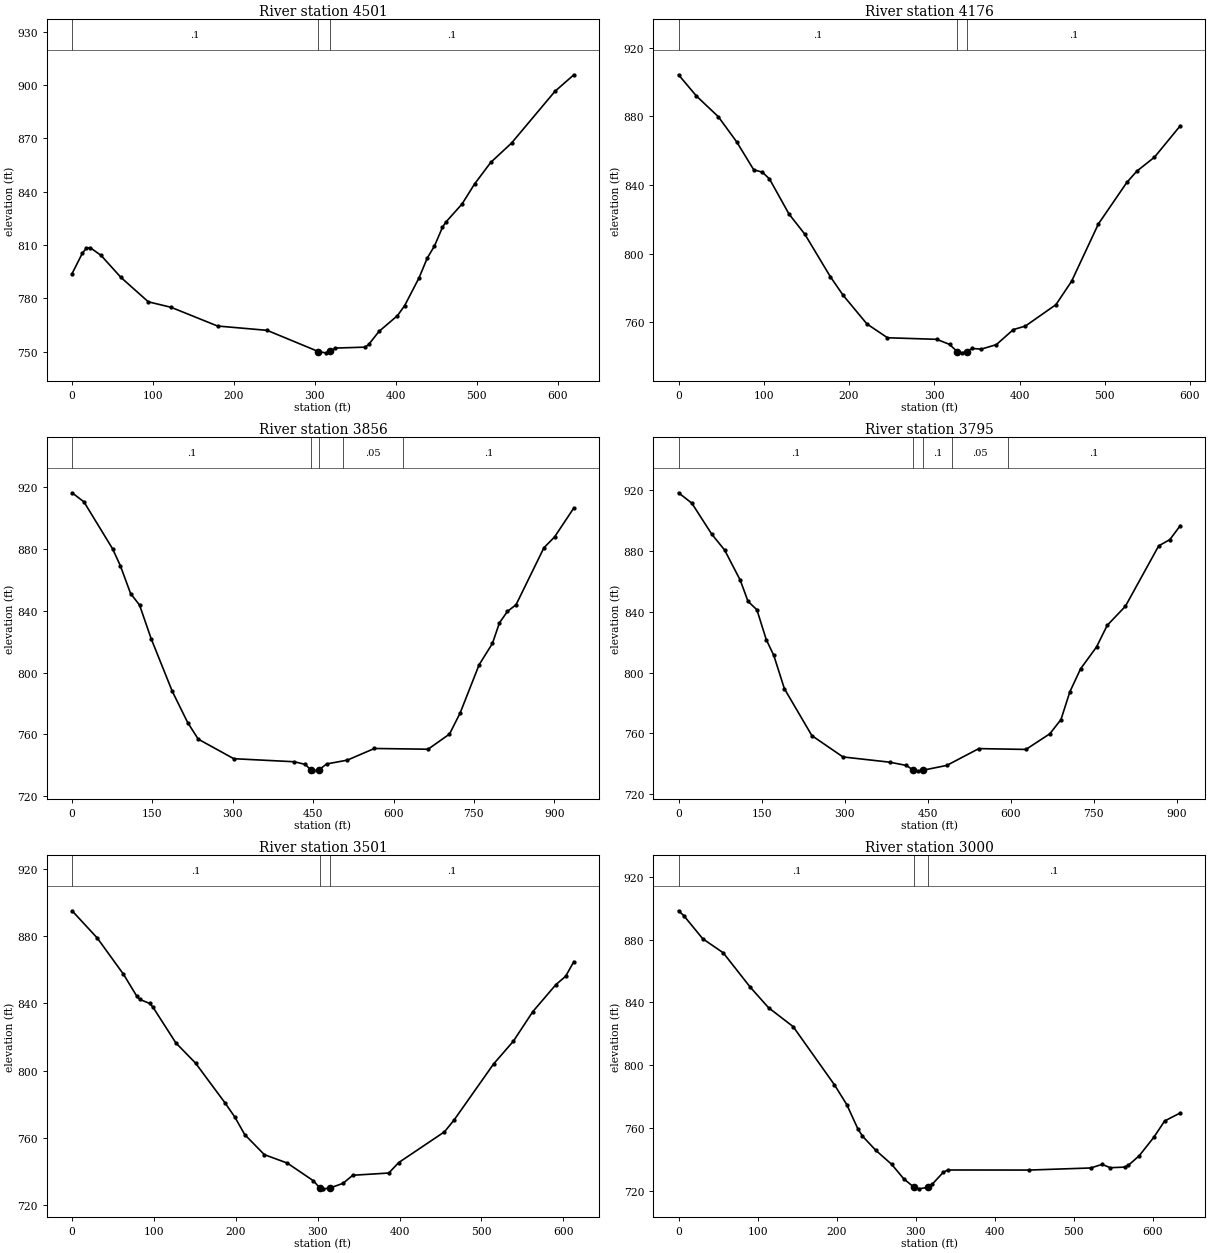
Type RM Length L Ch R = 1 ,4501    ,324.5,324.7,321.8
XS GIS Cut Line= 6
1607946.87190084410373.0607855021607792.30429658410473.261700585
1607727.54458359410513.5345859231607569.96353392410589.708646178
1607498.30882159410642.2777667491607424.95890267410703.526331916
#Sta/Elev= 30
       0   793.9    12.8  805.45    17.6  808.17    22.3  808.53    35.9   804.1
    60.4  791.76    94.2  778.05   122.4  774.96   179.7  764.45     241  762.01
   304.3  750.09   313.1  749.37  318.11750.1276   325.2  752.05     362  752.57
   366.5   754.1   379.1  761.38     402  770.29   410.9  775.94   428.7  791.58
   438.8  802.65   447.7  809.44   457.6  819.96   461.7  822.83   481.8  833.07
   497.3  844.34   517.2  856.42   542.9  867.29   596.5  896.36   619.9  905.69
#Mann= 3 ,-1,0
       0      .1       0   304.3    .045       0  318.11      .1       0
Bank Sta=304.3,318.11
XS Rating Curve= 0 ,0
Exp/Cntr(USF)=0,0
Exp/Cntr=0.3,0.1

Type RM Length L Ch R = 1 ,4176    ,310.6,320,327.3
BEGIN DESCRIPTION:
Structure 4 XS 4
END DESCRIPTION:
XS GIS Cut Line= 2
1607798.75503608410085.8231560531607327.17362527410438.122210013
#Sta/Elev= 30
       0  904.23      21  891.85    46.7  879.78    68.2  865.15    88.2  848.87
    98.2   847.5   106.7  843.52   129.6  823.07   148.1  811.37     178  786.63
     193  775.79     221  759.03   245.1  750.99   302.9  750.07   317.9  747.12
   326.8  742.91   332.8   742.2   338.7  742.95   343.9  744.75   355.3  744.39
   372.8  746.98   392.7  755.75   406.8  757.78   442.7  770.28   461.1  783.95
   492.5  817.32   525.8  841.46   537.5  848.04   558.3  856.22   588.6  874.55
#Mann= 3 ,-1,0
       0      .1       0   326.8    .045       0   338.7      .1       0
Bank Sta=326.8,338.7
XS Rating Curve= 0 ,0
Exp/Cntr(USF)=0,0
Exp/Cntr=0.3,0.1

Type RM Length L Ch R = 1 ,3856    ,62.1,61.2,64.9
BEGIN DESCRIPTION:
Structure 4 XS 3
END DESCRIPTION:
XS GIS Cut Line= 6
1607722.93214258409988.7328655921607447.38065155410172.742082752
1607371.55775805410108.0152224441607337.34498903410083.049147754
1607274.46746759410026.6443123431606896.27766951410009.075593117
#Sta/Elev= 30
       0  916.06    22.1  910.22    75.5  879.97      90  869.06   109.2  851.02
   125.9  843.59   147.7  821.77   186.9  787.97   215.7  767.73   235.5  756.99
   301.8  744.37   414.5   742.4   435.3  740.68   445.2  737.22   450.2  736.53
  460.98737.2122   475.1  740.99   513.5  743.42   564.3  750.97   664.4  750.49
   704.4  760.26   724.4  773.99   759.7  805.04   784.5  818.76   797.5  831.99
   812.5  839.46   828.6  843.77   880.6  880.54   900.6  887.59   936.5  906.28
#Mann= 5 ,-1,0
       0      .1       0   445.2    .045       0  460.98      .1       0
  505.62     .05       0  617.91      .1       0
Bank Sta=445.2,460.98
XS Rating Curve= 0 ,0
Exp/Cntr(USF)=0,0
Exp/Cntr=0.3,0.1

Type RM Length L Ch R = 1 ,3795    ,297.1,293.7,284.2
BEGIN DESCRIPTION:
Structure 4 XS 2
END DESCRIPTION:
XS GIS Cut Line= 6
1607707.21276222409966.5407992011607453.85333758410121.885263939
1607378.95511351410055.3090647651607344.74234449 410025.71964291
1607317.92693094409993.3562127571606897.20233894409958.218774304
#Sta/Elev= 30
       0  918.47    24.1   911.6    59.9  891.28    83.4   880.7   111.6  860.84
   125.6  846.93   141.6  841.44   158.5   821.8   172.2   811.3   191.3  789.43
     241  758.52   297.2  744.48   381.5  741.04   411.7  738.89   424.1  735.82
   432.9  735.33   442.6  735.81   484.7  738.89   542.7  749.97   627.9  749.43
   671.1  759.75   691.2  769.11   707.2  787.34   726.6  802.51   755.4   816.9
   774.8  831.18   807.6  843.71   867.8  883.51   887.9  887.61   906.9  896.88
#Mann= 5 ,-1,0
       0      .1       0   424.1    .045       0   442.6      .1       0
  494.66     .05       0  594.66      .1       0
Bank Sta=424.1,442.6
XS Rating Curve= 0 ,0
Exp/Cntr(USF)=0,0
Exp/Cntr=0.3,0.1

Type RM Length L Ch R = 1 ,3501    ,506.6,501.3,494.2
BEGIN DESCRIPTION:
Structure 4 XS 1
END DESCRIPTION:
XS GIS Cut Line= 6
1607586.88180718409757.8054543441607405.58394143409758.758536428
1607330.58835651409757.763459668   1607230.61021409755.679802418
 1607155.5850976409756.1046703461606974.18421367409759.456697762
#Sta/Elev= 30
       0  895.07    30.8  878.87    62.8  857.32    78.8  844.49    82.8  842.35
    94.8  839.97    98.8  837.74   126.8   816.5   150.8  804.51   186.8  780.85
   198.8  772.42   210.8  762.05   234.8  750.09   262.8  745.08   294.8  734.53
  302.61  730.25   306.8  729.76   314.8  730.25   330.8     733   342.8  737.83
   386.8  739.16   398.8  745.34   454.8  763.66   466.8  770.86   514.8  804.02
   538.8  817.46   562.8  835.19   590.8  851.12   602.8  856.17   612.8  864.84
#Mann= 3 ,-1,0
       0      .1       0  302.61    .045       0   314.8      .1       0
Bank Sta=302.61,314.8
XS Rating Curve= 0 ,0
Exp/Cntr(USF)=0,0
Exp/Cntr=0.3,0.1

Type RM Length L Ch R = 1 ,3000    ,496.7,505.4,510
XS GIS Cut Line= 6
1607487.60346243409084.267103255  1607290.747885409248.315331593
1607212.28872433409310.3696694231607150.59002884409353.484740675
   1607076.71288409406.7087155881606978.84791826409462.055061594
#Sta/Elev= 30
       0  898.36     6.7  895.24    30.6  880.57    56.6   871.6    90.7  849.77
   113.9  836.67   145.1  824.61   197.2  787.67   212.9     775     227   759.5
   232.7  754.97   249.8  745.82   269.7  736.99   285.1  727.72   298.1  722.35
   303.8  721.39   315.7  722.31   320.9  724.26   335.2  732.01   340.9  733.39
   443.6  733.34   521.5  734.67   536.1  736.96   546.3  734.84   564.7  735.22
   569.2  736.36     583  742.45   601.4  754.16   615.2  764.62     635   769.7
#Mann= 3 ,-1,0
       0      .1       0   298.1    .045       0   315.7      .1       0
Bank Sta=298.1,315.7
XS Rating Curve= 0 ,0
Exp/Cntr(USF)=0,0
Exp/Cntr=0.3,0.1

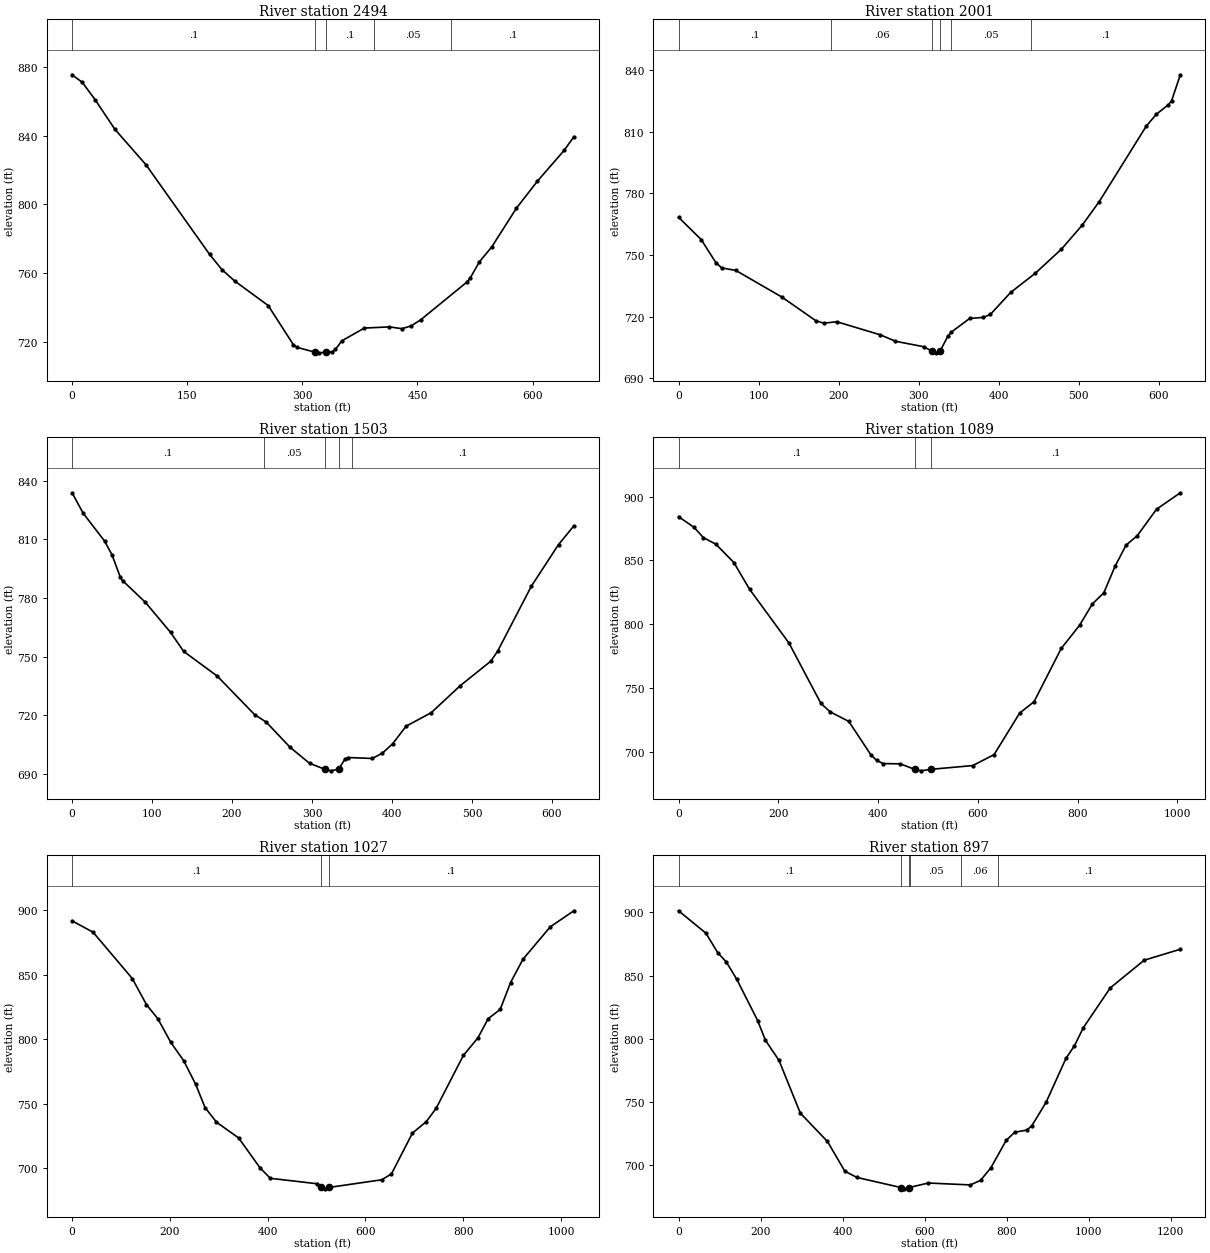
Type RM Length L Ch R = 1 ,2494    ,499.4,493.2,486
XS GIS Cut Line= 6
1607300.66420376408902.7349860071607203.38651118408936.139118671
1607034.20640334408956.759484261  1606860.158195408909.231364086
1606764.17085418408917.4672400061606663.86232775408941.509514749
#Sta/Elev= 30
       0  875.46    13.3  871.06    30.2  860.85    55.6  843.82    96.3  823.04
   179.1  770.89   195.1  762.04   211.7   755.4   255.5  741.06   288.3  718.25
   292.5  716.79  316.71  713.84     322  713.51   330.5  713.84   338.9  713.98
   343.1   715.5   351.5  720.53   380.8  727.94   413.5  728.62   429.8  727.57
     442  729.26   454.3  732.79   514.5  754.77   518.5   756.9   530.5  766.46
   546.6  775.11   578.9  797.77   606.2   813.5   641.1  831.46   653.7  839.34
#Mann= 5 ,-1,0
       0      .1       0  316.71    .045       0   330.5      .1       0
  393.84     .05       0  494.21      .1       0
Bank Sta=316.71,330.5
XS Rating Curve= 0 ,0
Exp/Cntr(USF)=0,0
Exp/Cntr=0.3,0.1

Type RM Length L Ch R = 1 ,2001    ,501.4,497.8,492.8
XS GIS Cut Line= 6
1606977.41091326 408382.56378226  1606894.181749 408438.25986509
1606818.29246509408492.7131682491606757.56522433408540.370553255
1606676.07260518408598.4219463321606467.88338901408747.607671589
#Sta/Elev= 30
       0  768.41    28.3  757.55    46.7  746.27    53.9  743.76    71.6   742.5
   129.1  729.54   171.6  717.99   181.5  716.82   197.8   717.5   252.3  711.11
     271  708.01   306.3  705.34   316.7  703.19   321.6  702.36  326.86 703.232
   336.4  710.44   340.7  712.43   363.7  719.11   380.9  719.63   389.5  721.05
     415  731.81   445.8  741.15   478.4   752.9   504.2  764.51   525.5  775.98
   584.4  812.84   597.1  818.67   611.9  823.19     616  825.19   626.9  837.83
#Mann= 6 ,-1,0
       0      .1       0  190.15     .06       0   316.7    .045       0
  326.86      .1       0  340.74     .05       0   440.8      .1       0
Bank Sta=316.7,326.86
XS Rating Curve= 0 ,0
Exp/Cntr(USF)=0,0
Exp/Cntr=0.3,0.1

Type RM Length L Ch R = 1 ,1503    ,420.3,414.1,397.3
BEGIN DESCRIPTION:
Structure 3 XS 4
END DESCRIPTION:
XS GIS Cut Line= 6
1606564.36154251 407988.523231761606505.99781409408066.860345423
1606451.18394734408140.8913653341606406.07511367   408206.511969
1606367.24546692408300.5304817561606283.42083143408542.682228416
#Sta/Elev= 30
       0  833.87    13.8  823.44    40.6  809.17    49.9  802.13    60.2  790.81
    63.1  788.93    91.7  777.77   123.1  762.42   139.6  752.63   181.5  740.03
   228.2  720.31   242.8  716.46   272.5  703.59     297  695.35  315.68  692.37
   323.6  691.51  333.28  692.37   340.9  697.33   345.2  698.33   375.4  697.84
   388.1  700.61   400.8  705.34   417.6  714.36   449.1  721.29   485.4  735.13
   523.5  747.64     532  752.71   574.3  786.08   608.2  807.34   627.4  816.93
#Mann= 5 ,-1,0
       0      .1       0   239.8     .05       0  315.68    .045       0
  333.28     .05       0  349.43      .1       0
Bank Sta=315.68,333.28
XS Rating Curve= 0 ,0
Exp/Cntr(USF)=0,0
Exp/Cntr=0.3,0.1

Type RM Length L Ch R = 1 ,1089    ,58.7,62.7,73.9
BEGIN DESCRIPTION:
Structure 3 XS 3
END DESCRIPTION:
XS GIS Cut Line= 6
 1606431.0596494407728.8712228451606061.49879964407943.404428007
1606078.72409348408012.3056033881606094.38345152408037.360576253
  1606122.570296408056.151805903 1605856.3612093408411.619233434
#Sta/Elev= 30
       0  884.31    31.2  875.92    49.7  867.89    75.1  862.66   110.9  848.32
   142.4  827.35   221.4  785.16   285.5  737.75     304  731.18   341.4  723.64
   385.3  697.64     397  693.08   410.4  690.53   444.6  690.36   473.7     686
   486.3  684.86   505.6  686.04   589.8  688.98   632.7  697.58   684.1  730.26
   712.7  739.03   767.4  780.95   804.1  799.09   829.8  815.85   852.7  824.55
   875.5   845.6   897.3  861.98   919.8  869.38   958.4  890.16  1006.1  903.06
#Mann= 3 ,-1,0
       0      .1       0   473.7    .045       0   505.6      .1       0
Bank Sta=473.7,505.6
XS Rating Curve= 0 ,0
Exp/Cntr(USF)=0,0
Exp/Cntr=0.3,0.1

Type RM Length L Ch R = 1 ,1027    ,113.7,129.7,147.7
BEGIN DESCRIPTION:
Structure 3 XS 2
END DESCRIPTION:
XS GIS Cut Line= 6
1606418.53216297407706.9481215881606001.99323908407949.668171224
1606016.08666132407966.8934650691606025.48227614408012.305603388
1606072.46035026408071.8111639441605826.60842902408386.564260568
#Sta/Elev= 30
       0  891.72    42.9  882.94   123.2  847.02   152.1  826.83   175.5  815.82
     202  797.47   228.2  783.39   252.8  765.04     272  746.99   295.4  735.65
   340.8  723.39   384.5   700.2   405.6  692.12   501.3  687.91   510.1   685.1
   518.3  683.96  524.63685.0011   633.5  690.99   653.3  695.52   696.2  727.16
   724.6  736.08   744.7   746.4   800.5  787.46   830.1  800.98   851.2  815.93
   875.7  823.04   896.9  843.89   922.3  861.97   978.1  887.07  1026.4  899.54
#Mann= 3 ,-1,0
       0      .1       0   510.1    .045       0  524.63      .1       0
Bank Sta=510.1,524.63
XS Rating Curve= 0 ,0
Exp/Cntr(USF)=0,0
Exp/Cntr=0.3,0.1

Type RM Length L Ch R = 1 ,897     ,53.9,56.7,56.8
BEGIN DESCRIPTION:
Structure 2 XS 3
END DESCRIPTION:
XS GIS Cut Line= 6
1606407.57061234407667.7997264851605994.16356006407927.745069966
  1605970.674523407901.124161296 1605893.9436686407854.146087173
1605834.43810804 407807.168013051605687.24014246408320.794956796
#Sta/Elev= 30
       0  901.23    66.9   883.5    95.9  867.97   116.2  860.94   142.3  846.96
   193.1  814.37   211.8  798.99   245.1  782.98     297  741.37   363.2  718.94
   405.7  695.42   435.3  690.52   543.6  682.48   550.3  681.53  561.26682.4849
   609.3  686.12   711.9  684.62   736.8   688.3   761.8  698.15   799.3  719.89
     820  726.25   849.2  727.94   861.7  731.39   896.4  749.83   944.9  784.57
   965.7  794.55   986.9  808.64  1053.1  840.31  1135.7  862.16  1223.9  870.84
#Mann= 6 ,-1,0
       0      .1       0   543.6    .045       0  561.26      .1       0
  563.84     .05       0  689.63     .06       0  779.63      .1       0
Bank Sta=543.6,561.26
XS Rating Curve= 0 ,0
Exp/Cntr(USF)=0,0
Exp/Cntr=0.3,0.1

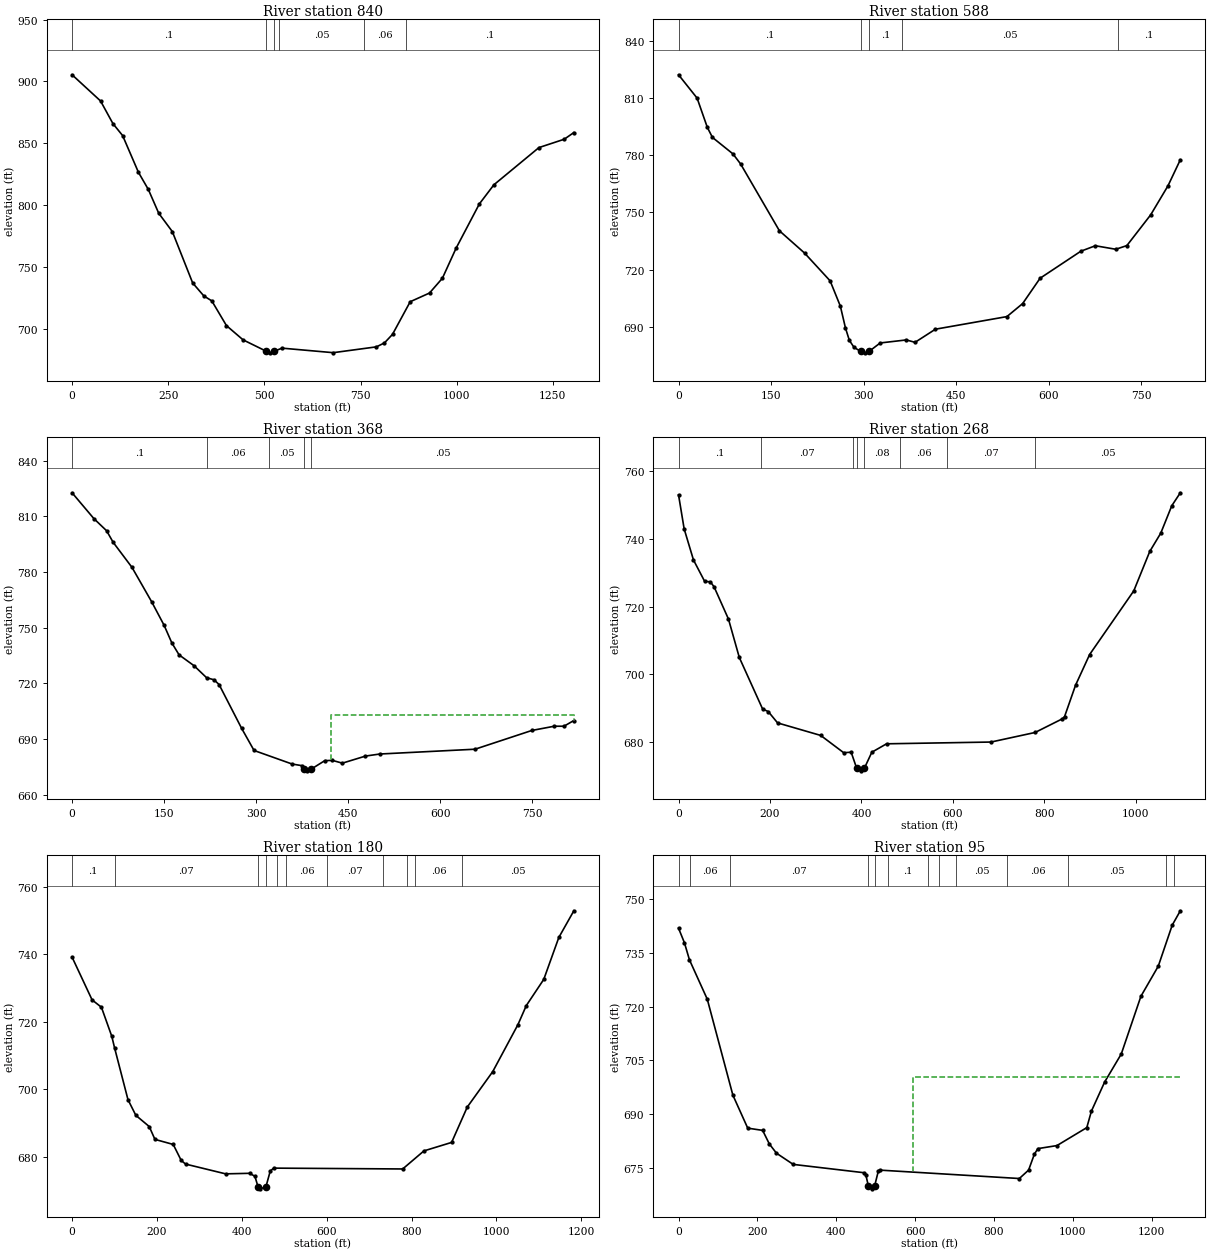
Type RM Length L Ch R = 1 ,840     ,262.8,252.3,242.4
BEGIN DESCRIPTION:
Structure 2 XS 2
END DESCRIPTION:
XS GIS Cut Line= 6
1606396.60906171407645.876625228 1606009.8229181407865.107637802
  1605970.674523407847.8823439571605914.30083405407805.602077246
1605836.00404384407713.2118648041605652.78955476408311.399341971
#Sta/Elev= 30
       0  905.36    74.1  884.18   106.3  865.86   131.4  856.25   172.5  826.57
   198.3  812.68   225.3  793.46   260.6  778.68   313.6  737.09   342.7  726.62
   363.3  722.64   401.4  702.66   444.6  691.15  505.22   681.9   515.6  680.66
   525.6   681.9   545.6  684.46     679  680.79   791.3   685.5   812.2   688.7
   833.1   695.6   879.1  721.97   929.3  728.99   962.8  740.94   998.6  765.35
    1059  801.05  1096.7  816.46  1213.8  846.53  1279.6  853.28  1304.6  858.69
#Mann= 6 ,-1,0
       0      .1       0  505.22    .045       0   525.6      .1       0
  537.37     .05       0  759.02     .06       0  869.02      .1       0
Bank Sta=505.22,525.6
XS Rating Curve= 0 ,0
Exp/Cntr(USF)=0,0
Exp/Cntr=0.3,0.1

Type RM Length L Ch R = 1 ,588     ,218.4,219.6,221.9
BEGIN DESCRIPTION:
Structure 2 XS 1
END DESCRIPTION:
XS GIS Cut Line= 3
1606077.15815768407556.6182843941605814.08094259407628.651331383
1605355.26175199407915.217583533
#Sta/Elev= 30
       0  822.32    30.1  810.06    46.7  794.67      55  789.41    88.2  780.77
   100.6   775.5   163.6  740.36   204.3  728.68   245.8  714.06   262.4  700.78
   270.7  689.29     277   682.8   284.5  679.15   295.2  677.02   302.7  676.24
   308.9  676.97     327  681.43   369.4  683.02   383.5  681.76   416.6  688.66
   532.5  695.28     558  702.12   586.3  715.43   652.4  729.63   675.9   732.5
     709  730.65     727  732.58   765.6  748.72   793.6  763.93   813.7  777.67
#Mann= 5 ,-1,0
       0      .1       0   295.2    .045       0   308.9      .1       0
  362.76     .05       0  712.76      .1       0
Bank Sta=295.2,308.9
XS Rating Curve= 0 ,0
Exp/Cntr(USF)=0,0
Exp/Cntr=0.3,0.1

Type RM Length L Ch R = 1 ,368     ,100.3,100.9,101.2
BEGIN DESCRIPTION:
Structure1 XS 4
END DESCRIPTION:
XS GIS Cut Line= 4
 1606047.4053774407495.5467880341605760.83912525407440.739034891
1605504.02565338 407501.810531251605255.18483315407583.849794948
#Sta/Elev= 30
       0  822.71    35.6  808.76    56.3  802.23    66.9  796.03    97.7  782.46
   129.6     764     150  751.25   162.6  741.75   174.4  735.31   198.8  729.45
   219.2     723   231.4  721.86   239.6   719.3   276.2  695.77   296.6  683.75
   358.6  676.44   374.7  675.56   378.6  673.77     383  672.77   390.1  673.77
   411.8  678.25   424.1  678.42   440.5  676.91   478.2  680.73   501.5  681.84
   656.7  684.43   749.4  694.55   785.9  696.83   801.7  696.83   817.8  699.91
#Mann= 5 ,-1,0
       0      .1       0     220     .06       0  321.76     .05       0
   378.6    .045       0   390.1     .05       0
#XS Ineff= 2 , 0
                             422          703.14
Permanent Ineff=
       F       F
Bank Sta=378.6,390.1
XS Rating Curve= 0 ,0
Exp/Cntr(USF)=0,0
Exp/Cntr=0.3,0.1

Type RM Length L Ch R = 1 ,268     ,86.8,87.1,88.9
BEGIN DESCRIPTION:
Structure1 XS 3
END DESCRIPTION:
XS GIS Cut Line= 6
 1606008.1612723407361.6384341781605796.75993875407317.792231663
1605698.10598309407356.9406267661605597.88609163407380.429663827
1605253.38021472407388.2593428481605035.71513795407632.545328287
#Sta/Elev= 30
       0  752.92    12.3  742.88    32.7  733.71    57.2  727.39    69.5  727.29
    77.7  725.81   109.2  716.29   132.9  704.97   183.9  689.76   196.1  689.04
   216.6  685.68   310.9  681.99   361.1   676.9   377.5  677.04  389.57   672.3
     398  671.55   406.3  672.29   422.7  677.04   454.9  679.52   683.3  680.04
   779.7  682.86   839.2  686.88   844.1  687.52   868.2   696.8     899  705.85
   995.5  724.61  1030.5  736.24  1054.5  741.62  1078.6   749.7  1097.3  753.53
#Mann= 8 ,-1,0
       0      .1       0     180     .07       0  382.04     .08       0
  389.57    .045       0   406.3     .08       0  484.97     .06       0
  587.84     .07       0  780.09     .05       0
Bank Sta=389.57,406.3
XS Rating Curve= 0 ,0
Exp/Cntr(USF)=0,0
Exp/Cntr=0.3,0.1

Type RM Length L Ch R = 1 ,180     ,84.3,85.4,86.6
BEGIN DESCRIPTION:
Structure1 XS 2
END DESCRIPTION:
XS GIS Cut Line= 6
1606020.68875873407327.1878464881605776.40277329407242.627313066
 1605704.3697263407273.9460291481605532.11678785407299.001002014
1605264.34176535407294.3031946021605004.39642187407602.792548009
#Sta/Elev= 30
       0  739.19    47.2  726.49    69.2  724.31    93.7  715.65     100  712.34
   131.8  696.86   150.3  692.22   181.8   688.9   195.3  685.08   238.4  683.58
   257.2  678.84   267.5  677.75   361.9  674.85   418.3  675.01   430.9  674.13
  438.32670.9819     443   670.4   456.8  670.98   467.1  675.69   475.2  676.55
   779.2   676.3   829.2  681.66   894.5  684.18   931.4  694.68   991.4   705.2
  1050.7  719.12  1070.5   724.8  1111.7  732.59  1147.2  745.04  1182.6  752.95
#Mann= 11 ,-1,0
       0      .1       0     100     .07       0  438.32    .045       0
   456.8     .07       0  483.28     .08       0  503.28     .06       0
  601.39     .07       0  732.57     .05       0  789.23     .07       0
  809.23     .06       0  919.23     .05       0
Bank Sta=438.32,456.8
XS Rating Curve= 0 ,0
Exp/Cntr(USF)=0,0
Exp/Cntr=0.3,0.1

Type RM Length L Ch R = 1 ,95      ,,,
BEGIN DESCRIPTION:
Structure1 XS 1
END DESCRIPTION:
XS GIS Cut Line= 6
1606058.27121803407289.6053871891605840.60614126407214.440468592
1605629.20480771407211.3085969841605388.05069388407195.649238943
1605195.44058997407216.0064043961604926.09963167407505.704528155
#Sta/Elev= 30
       0  741.87      15  737.79    27.7  733.04    72.9  722.06   137.8   695.3
   175.5  686.09   213.3  685.47   230.3  681.68   248.4   679.1   290.8  675.98
   470.9  673.65   474.9  673.13  481.59669.8738   490.9  669.16  497.04669.8478
   506.9  674.21   510.9  674.38   864.3  672.04   887.8  674.39   902.4  678.82
   911.3  680.38   959.7  681.23  1035.4  686.24  1047.1  690.84  1080.7  698.97
  1122.8  706.77  1172.7  722.89  1216.6  731.26    1252  742.71  1272.6  746.73
#Mann= 13 ,-1,0
       0      .1       0      30     .06       0     130     .07       0
  481.59    .045       0  497.04     .07       0   531.7      .1       0
   631.7     .05       0   661.7      .1       0  703.36     .05       0
  833.36     .06       0  987.05     .05       0 1237.05     .07       0
 1257.05      .1       0
#XS Ineff= 2 , 0
                          593.82          700.34
Permanent Ineff=
       F       F
Bank Sta=481.59,497.04
XS Rating Curve= 0 ,0
Exp/Cntr(USF)=0,0
Exp/Cntr=0.3,0.1
LCMann Table=0

Chan Stop Cuts=-1
Use User Specified Reach Order=0
Composite Channel Slope=5